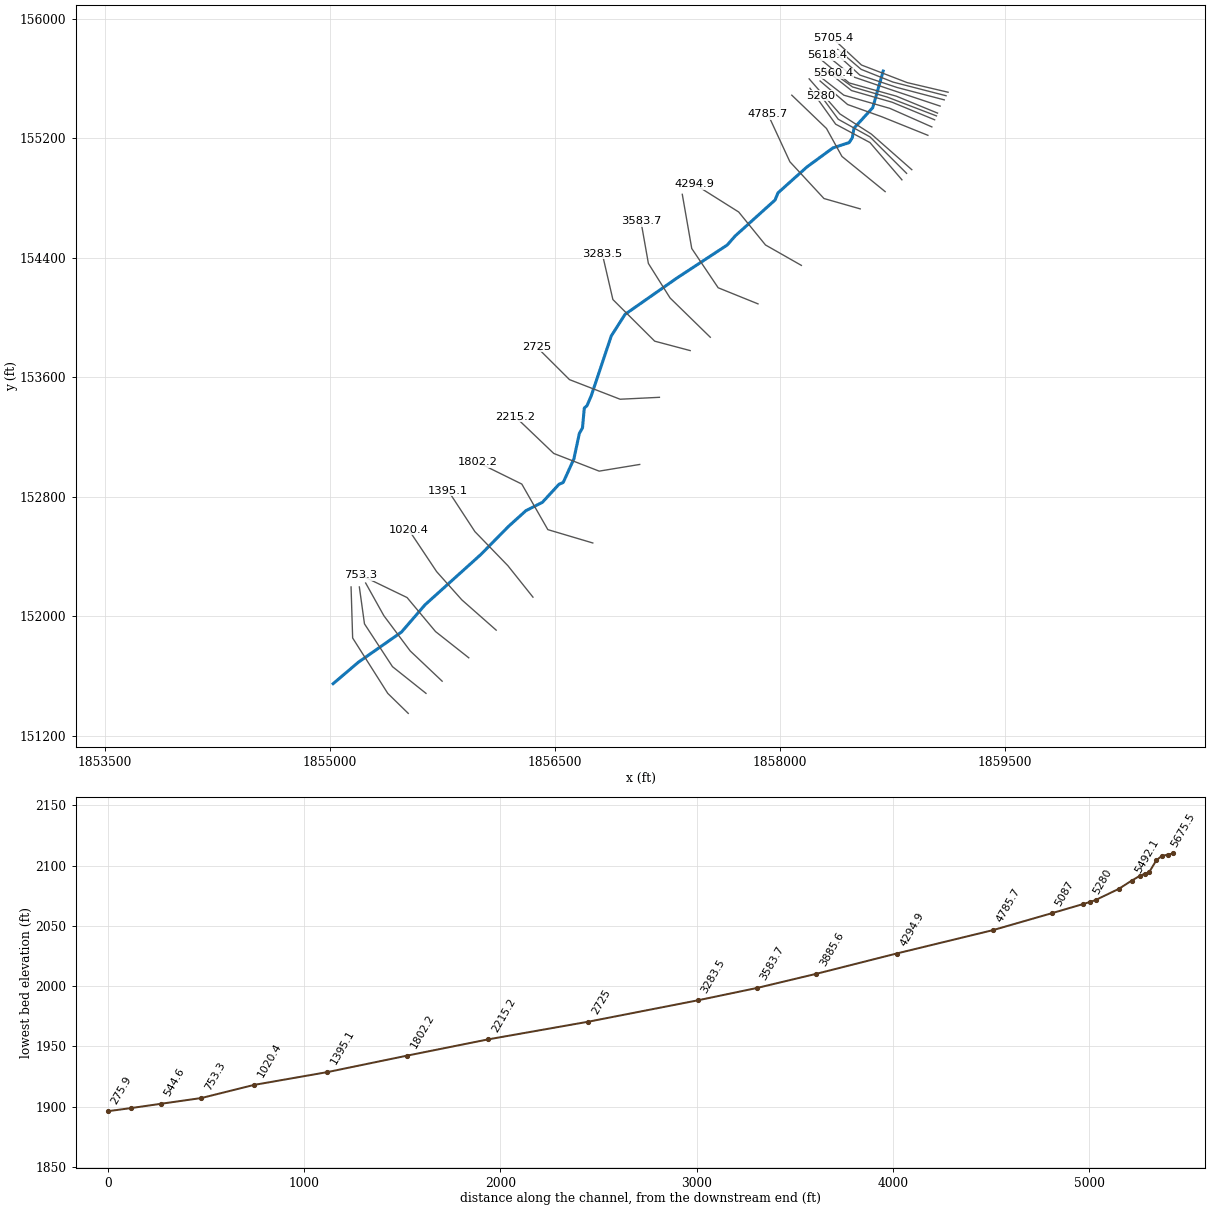
--- Bearwallow Branch.prj (project) ---

Proj Title=Bearwallow Branch
Current Plan=p01
Default Exp/Contr=0,0
English Units
Geom File=g01
Flow File=f01
Plan File=p01
BEGIN DESCRIPTION:
END DESCRIPTION:
DSS Export Rating Curves= 0
DSS Export Rating Curve Sorted= 0
DSS Export Volume Flow Curves= 0
DXF OffsetX= 0
DXF OffsetY= 0
DXF ScaleX= 0
DXF ScaleY= 0

--- Bearwallow Branch.p01 (plan) ---

Plan Title=Floodplain
Program Version=4.00
Geom File=g01
Flow File=f01
K Sum by GR=0
Std Step Tol=0.01
Critical Tol=0.01
Num of Std Step Trials=20
Max Error Tol=0.3
Flow Tol Ratio=0.001
Split Flow NTrial=30
Split Flow Tol=0.02
Split Flow Ratio=0.02
Log Output Level=0
Friction Slope Method=1
Unsteady Friction Slope Method=2
Unsteady Bridges Friction Slope Method=1
Global Log Level=0
CheckData=False
Run HTab=0
Run UNet=0
Run PostProcess=0
UNET Theta=0
UNET Theta Warmup=0
UNET ZTol=0
UNET ZSATol=0
UNET MxIter=0
UNET MaxInSteps=0
UNET DtIC=0
UNET DtMin=0
UNET MaxCRTS=0
UNET WFStab=0
UNET SFStab=0
UNET WFX=0
UNET SFX=0
UNET DSS MLevel=0
UNET DZMax Abort=0
UNET Convert EG Bridges=0
UNET Use Existing IB Tables=0
UNET Froude Limit=0
UNET Froude Power=0
Write IC File=0
Echo Input=False
Echo Output=False
Write Detailed=0

--- Bearwallow Branch.f01 (steady flow) ---

Flow Title=NFF Regression Equation
Program Version=4.00
Number of Profiles=1
Profile Names=P100yr
River Rch & RM=Bearwallow Br...,Main      ,5705.4
552.7876
River Rch & RM=Bearwallow Br...,Main      ,5087
564.5214
River Rch & RM=Bearwallow Br...,Main      ,4785.7
712.1162
River Rch & RM=Bearwallow Br...,Main      ,3583.7
732.7405
River Rch & RM=Bearwallow Br...,Main      ,3283.5
848.8095
River Rch & RM=Bearwallow Br...,Main      ,275.9
922.5498
Boundary for River Rch & Prof#=Bearwallow Br...,Main      ,1
Up Type=0
Dn Type=3
Dn Slope=0.020964

--- Bearwallow Branch.g01 (geometry) ---

Geom Title=USGS 10m DEM
Program Version=4.00

River Reach=Bearwallow Br...,Main
Reach XY= 30
      1858686.65      155649.284     1858617.141      155404.468
     1858492.135      155267.146     1858481.052      155203.646
     1858460.166      155170.634     1858351.695      155134.926
     1858178.545       155007.59     1857985.184      154833.767
     1857966.319      154786.605     1857700.156      154545.514
     1857646.969      154484.772     1857312.822      154264.526
     1856965.825       154020.57     1856874.197      153876.391
     1856740.027      153474.132     1856711.827       153408.82
      1856694.31      153393.324     1856682.183      153260.598
     1856661.297      153223.543     1856624.916      153053.089
       1856553.5      152894.761     1856525.877      152883.308
     1856414.711      152762.036     1856305.566      152706.789
     1856188.336       152600.34     1856003.862      152412.173
     1855632.506      152076.175     1855475.526      151893.593
     1855187.168      151690.799     1855019.716      151547.885

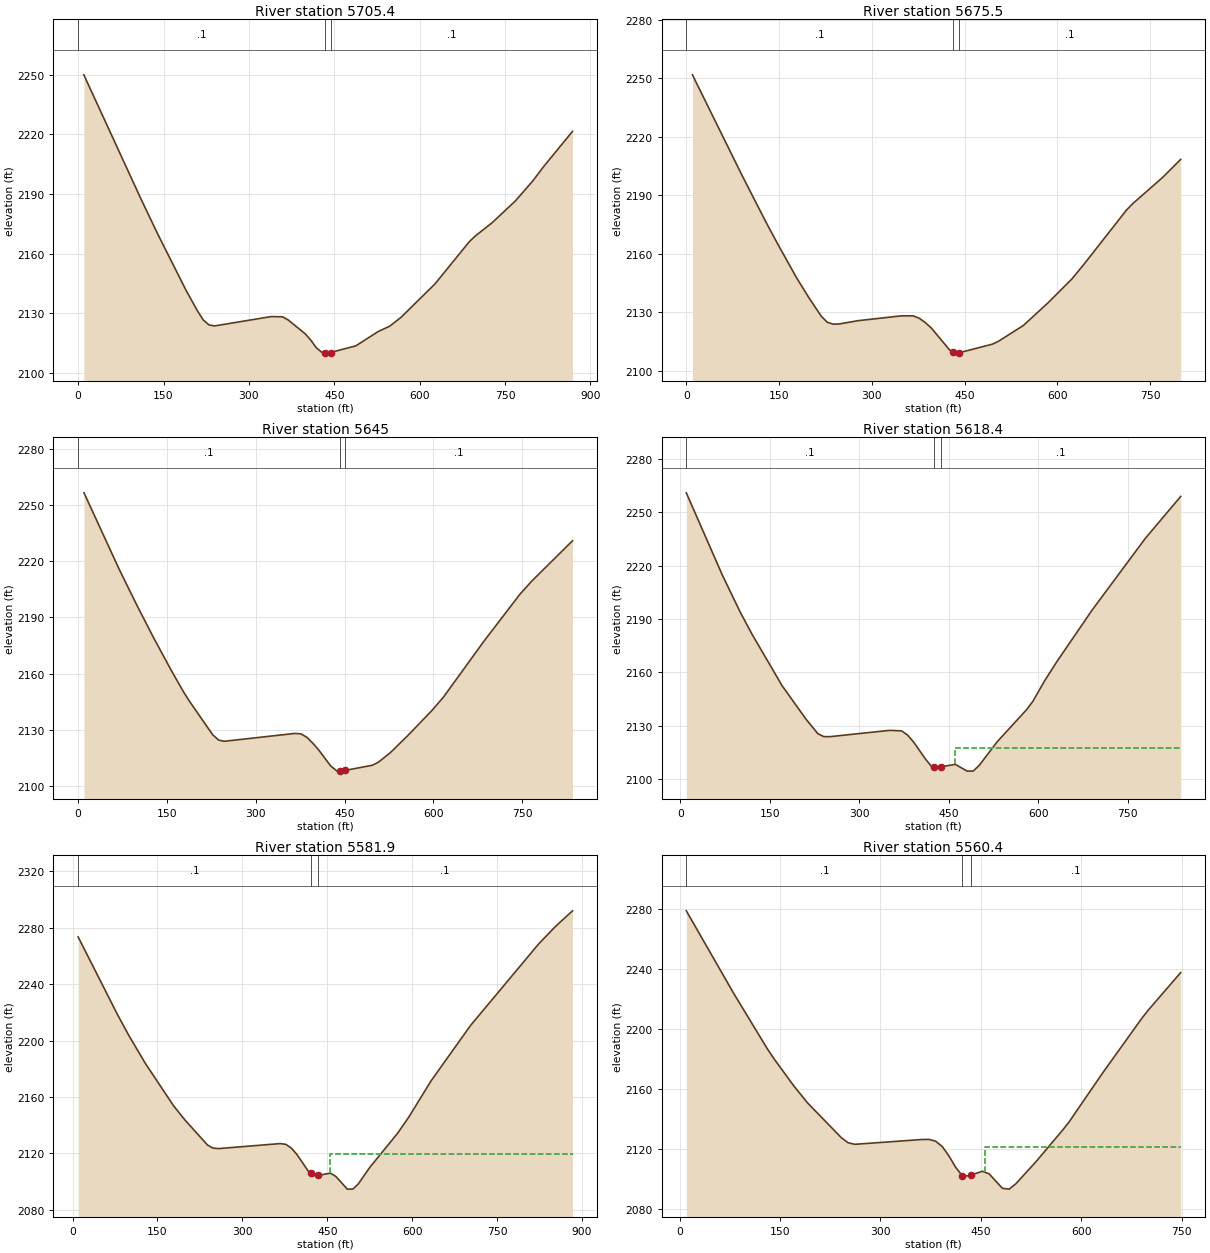
Type RM Length L Ch R = 1 ,5705.4  ,30.2,29.9,29.6
XS GIS Cut Line= 4
     1859119.414      155507.686     1858847.033      155572.006
     1858542.121      155689.765     1858350.763      155868.506
#Sta/Elev= 30
      10    2250   109.9 2187.89   139.9 2169.91   189.9 2141.49   209.9 2131.19
   219.9 2126.72   229.9 2124.24   239.9 2123.75   339.3 2128.44   359.1 2128.32
     369 2126.76   398.7 2119.83   408.6 2116.67   418.5 2112.75   428.4 2110.43
   433.4 2110.24   438.3 2110.06   443.4 2110.37   487.9 2113.72   527.5 2120.97
   547.3 2123.59   567.1 2128.01   626.9 2144.85   687.3 2166.11   697.4 2168.87
   727.6  2175.7   767.9  2186.5   798.1 2196.41   818.2 2203.98   868.6 2221.58
#Mann= 3 , 0 , 0
       0      .1       0   433.4    .045       0   443.4      .1       0
Bank Sta=433.4,443.4
XS Rating Curve= 0 ,0
Exp/Cntr=0.3,0.1

Type RM Length L Ch R = 1 ,5675.5  ,29.3,30.5,31.6
XS GIS Cut Line= 4
     1859105.935      155484.226     1858750.911      155576.013
     1858539.629      155660.872     1858383.764      155794.223
#Sta/Elev= 30
     9.9 2251.71    89.2 2200.74   128.8  2176.2   148.7 2164.46   178.4 2147.59
   198.2 2137.44     218 2128.05   227.9 2124.84   237.9 2123.84   247.8 2123.99
   277.5 2125.63   346.9 2128.09   366.7 2128.14   376.6  2126.9   386.5 2124.68
   396.4 2121.82   426.1 2110.51     431 2109.76     436    2109     441 2109.18
   495.4 2113.63   505.3 2115.17   544.9 2123.14   584.5 2134.65   623.7 2147.08
   643.2 2154.62   711.6 2182.27   721.4  2185.5   770.2 2199.08   799.5 2208.34
#Mann= 3 , 0 , 0
       0      .1       0     431    .045       0     441      .1       0
Bank Sta=431,441
XS Rating Curve= 0 ,0
Exp/Cntr=0.3,0.1

Type RM Length L Ch R = 1 ,5645    ,26.7,26.6,26.4
XS GIS Cut Line= 4
     1859093.812      155456.517      1858778.62      155539.645
     1858530.969      155622.772     1858347.396      155789.027
#Sta/Elev= 30
     9.9 2256.58    69.1 2215.89    98.8 2196.78   128.4 2178.57     158  2161.3
   177.8 2150.33   187.7 2145.37   227.2 2127.32   237.1  2124.5   246.9 2123.83
   366.2 2128.03   376.2 2127.79   386.3 2125.96   396.3 2122.81   406.3 2119.17
   426.4 2110.68   436.5 2108.09   441.5 2107.99   446.5 2107.88   451.5 2108.31
   496.8 2111.02   506.8 2112.59   526.9 2117.65   557.1    2127   597.1 2140.16
   616.9 2147.41   686.3 2177.72   745.7 2202.24   765.5 2209.24   834.9 2230.98
#Mann= 3 , 0 , 0
       0      .1       0   441.5    .045       0   451.5      .1       0
Bank Sta=441.5,451.5
XS Rating Curve= 0 ,0
Exp/Cntr=0.3,0.1

Type RM Length L Ch R = 1 ,5618.4  ,35.4,36.6,37.7
XS GIS Cut Line= 4
     1859066.103      155414.953     1858714.543      155532.717
     1858487.674      155610.649     1858311.028      155754.391
#Sta/Elev= 30
      10 2260.95    70.1 2214.86   100.2  2193.9   120.2 2181.34   170.3 2152.53
   210.4 2133.65   230.5 2125.39   240.5 2123.75   250.5 2123.72   350.7 2127.27
   370.8 2126.98   380.8 2124.61   390.7 2120.78   410.7 2111.15   420.7 2107.05
  424.67 2106.75   430.7 2106.24  437.51 2106.76   460.7 2108.16   480.7 2104.33
   490.7 2104.37   500.7 2107.53   530.7 2120.77   580.7 2139.12   590.7 2143.62
   610.6 2155.27   630.4 2165.69   689.9 2194.93     779 2235.26   838.4 2258.91
#Mann= 3 , 0 , 0
      10      .1       0  424.67    .045       0  437.51      .1       0
#XS Ineff= 2 , 0
                          459.55         2117.17
Permanent Ineff=
       F       F
Bank Sta=424.67,437.51
XS Rating Curve= 0 ,0
Exp/Cntr=0.3,0.1

Type RM Length L Ch R = 1 ,5581.9  ,21.7,21.5,21.3
XS GIS Cut Line= 4
     1859048.905      155368.031     1858773.433      155481.584
     1858460.111      155569.903     1858260.341      155736.027
#Sta/Elev= 30
     9.9 2273.48    79.5 2218.34    99.3 2203.71   129.1 2183.48   178.8 2153.54
   198.6 2143.66   238.4 2125.89   248.3  2123.7   258.2 2123.36     367  2126.9
   376.9 2126.35   386.7 2123.64   396.6 2119.07   416.3 2107.46  421.13 2105.74
   426.2 2104.19  433.51 2104.34   455.8 2105.94   465.7 2103.41   485.4  2094.6
   495.3 2094.64   505.1 2098.42   524.8 2109.84   574.2  2134.2   593.9 2145.58
   633.5 2171.44   703.4 2210.81   823.3 2268.42   853.3 2280.96   883.3 2291.98
#Mann= 3 , 0 , 0
     9.9      .1       0  421.13    .045       0  433.51      .1       0
#XS Ineff= 2 , 0
                          454.73         2119.64
Permanent Ineff=
       F       F
Bank Sta=421.13,433.51
XS Rating Curve= 0 ,0
Exp/Cntr=0.3,0.1

Type RM Length L Ch R = 1 ,5560.4  ,24.4,24.5,24.6
XS GIS Cut Line= 4
     1859041.857      155349.144     1858712.811      155475.567
     1858482.478      155543.108     1858356.055      155634.895
#Sta/Elev= 30
    10.1 2278.55    80.6 2223.81   130.9 2186.89     141 2180.12   171.2 2161.71
   191.4 2150.59   241.7 2127.53   251.8 2124.15   261.9 2123.09   362.5  2126.3
   372.5 2126.37   382.5  2125.2   392.5 2121.63   402.5 2115.39   412.5 2107.83
   422.5 2102.15   432.5 2102.04  435.73 2102.65   452.5 2105.16   462.5 2103.44
   482.5 2093.78   492.5 2093.25   502.5 2096.81   532.5 2111.48   572.5  2132.6
   582.5 2138.28   631.6 2170.22   690.2 2206.67   699.9  2212.2   748.8 2237.44
#Mann= 3 , 0 , 0
    10.1      .1       0   422.5    .045       0  435.73      .1       0
#XS Ineff= 2 , 0
                          455.65         2120.98
Permanent Ineff=
       F       F
Bank Sta=422.5,435.73
XS Rating Curve= 0 ,0
Exp/Cntr=0.3,0.1

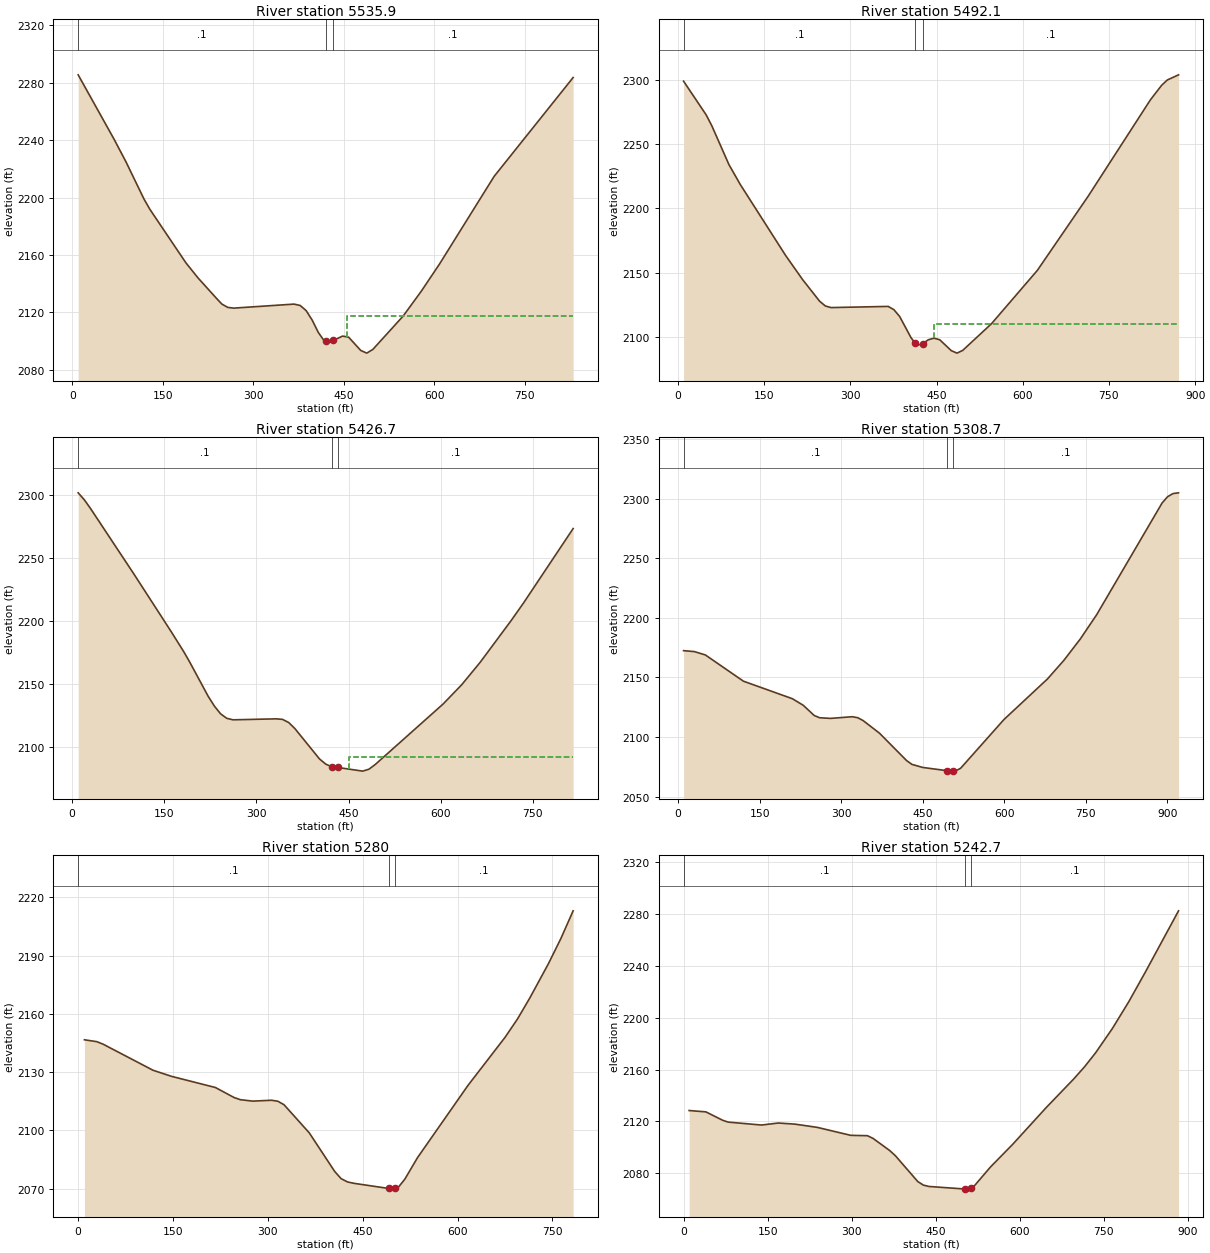
Type RM Length L Ch R = 1 ,5535.9  ,43.8,43.8,43.8
XS GIS Cut Line= 4
     1859029.734      155323.167     1858745.716      155440.931
     1858475.551      155518.863     1858286.782      155669.531
#Sta/Elev= 30
     9.9 2285.59    69.4 2240.72    89.3 2224.81     119    2199   128.9 2191.76
   188.4 2154.59   208.3 2144.16     238  2130.3     248 2125.82   257.9 2123.48
   267.8 2122.98   367.7 2125.78   377.8 2124.84   387.8 2121.22   397.8 2114.57
   407.9 2106.03   417.9 2100.01  420.97 2099.78     428 2099.37  432.49 2100.43
   448.1 2103.48   458.1 2102.75   478.2 2093.48   488.2 2091.61   498.3  2094.2
   548.5 2117.45   578.6  2134.8   608.8 2153.74   699.3 2214.83   830.2 2283.71
#Mann= 3 , 0 , 0
     9.9      .1       0  420.97    .045       0  432.49      .1       0
#XS Ineff= 2 , 0
                          454.79         2117.28
Permanent Ineff=
       F       F
Bank Sta=420.97,432.49
XS Rating Curve= 0 ,0
Exp/Cntr=0.3,0.1

Type RM Length L Ch R = 1 ,5492.1  ,66.7,65.5,64.9
XS GIS Cut Line= 4
     1859011.054      155275.506     1858731.377      155399.573
     1858424.363      155487.893     1858230.902      155639.297
#Sta/Elev= 30
     9.9 2298.76    49.3 2272.52    59.2 2263.97    88.8 2233.98   108.6 2218.43
   187.5 2163.29   217.1  2144.5   246.7  2127.7   256.6 2124.05   266.5 2122.81
   365.9 2123.71   375.8 2121.21   385.8 2115.94   405.8 2099.29  412.84 2095.29
   415.8 2093.56   425.8 2094.67   435.7 2097.79   445.7 2099.04   455.7 2097.77
   475.7 2089.33   485.7 2087.41   495.6 2089.55   545.6 2110.24   625.4 2151.68
   713.9 2209.38     822 2284.15   841.6 2295.51   851.4 2299.63   871.1 2303.69
#Mann= 3 , 0 , 0
     9.9      .1       0  412.84    .045       0   425.8      .1       0
#XS Ineff= 2 , 0
                          444.98         2110.22
Permanent Ineff=
       F       F
Bank Sta=412.84,425.8
XS Rating Curve= 0 ,0
Exp/Cntr=0.3,0.1

Type RM Length L Ch R = 1 ,5426.7  ,122.7,118,112.7
XS GIS Cut Line= 4
     1858984.707      155219.257     1858676.443      155343.949
     1858449.574      155425.344     1858266.001       155582.94
#Sta/Elev= 30
    10.1 2301.36    20.2 2295.78    30.2 2288.94   100.8 2236.96   161.2 2191.45
   181.4 2175.77   191.5 2167.24   221.7 2139.93   231.8 2132.18   241.8  2126.1
   251.9 2122.51     262 2121.31   332.5 2122.08   342.6 2121.66   352.6 2119.19
   362.7  2114.4   402.8 2090.28   412.9 2086.18   422.9 2084.05  428.36 2082.74
     433  2083.5   473.1 2080.61   483.2 2082.12   493.2 2085.74   603.8 2133.79
     634 2149.03   664.3 2166.97   714.7 2200.08   734.9 2214.07   815.5 2273.01
#Mann= 3 , 0 , 0
    10.1      .1       0   422.9    .045       0     433      .1       0
#XS Ineff= 2 , 0
                          450.57         2092.05
Permanent Ineff=
       F       F
Bank Sta=422.9,433
XS Rating Curve= 0 ,0
Exp/Cntr=0.3,0.1

Type RM Length L Ch R = 1 ,5308.7  ,27.4,28.7,30
XS GIS Cut Line= 4
      1858877.33      154989.216      1858607.17      155227.916
     1858397.727      155362.746     1858193.051       155597.24
#Sta/Elev= 30
      10 2172.41      30 2171.61    50.1 2168.81   120.2  2146.8   210.3  2132.1
   230.3 2126.58   250.4 2118.05   260.4 2116.15   280.4  2115.6   320.4    2117
   330.5 2116.19   340.5 2113.76   370.5 2103.23   420.3 2080.29   430.3 2077.03
   450.2 2074.46     495 2071.75     500 2071.38     505 2071.39     510  2071.4
   519.9  2073.8   599.6 2114.65   679.9 2148.77     710 2164.34   740.1  2182.2
   770.2 2202.52   890.7 2296.27   900.8 2301.54   910.8 2304.15   920.9 2304.76
#Mann= 3 , 0 , 0
      10      .1       0     495    .045       0     505      .1       0
Bank Sta=495,505
XS Rating Curve= 0 ,0
Exp/Cntr=0.3,0.1

Type RM Length L Ch R = 1 ,5280    ,36.9,37.2,37.5
XS GIS Cut Line= 4
     1858842.698      154964.679     1858598.511      155208.866
     1858387.228       155326.63     1858271.196      155484.226
#Sta/Elev= 30
     9.9 2146.68    29.6  2145.7    39.5 2144.41   118.4 2130.99     148 2127.82
   217.1  2122.1   246.7 2116.93   256.5 2115.83   276.3 2115.09   305.9 2115.54
   315.7 2115.04   325.6 2113.24   365.5 2098.77   405.8 2078.86   415.9 2075.16
     426 2073.48     436 2072.77   491.5  2070.1   496.5 2069.77   501.5 2070.28
   506.6  2070.8   516.7  2074.9   536.8 2086.01   616.6 2123.19   675.3 2147.99
   694.9  2157.4   714.4 2168.22   743.8 2185.85   763.4 2198.74   782.9 2213.09
#Mann= 3 , 0 , 0
       0      .1       0   491.5    .045       0   501.5      .1       0
Bank Sta=491.5,501.5
XS Rating Curve= 0 ,0
Exp/Cntr=0.3,0.1

Type RM Length L Ch R = 1 ,5242.7  ,167.4,155.7,144.1
XS GIS Cut Line= 4
     1858811.525      154921.384     1858598.511      155170.766
      1858369.91      155293.726     1858198.459      155534.449
#Sta/Elev= 30
     9.9 2128.44    39.8  2127.4    69.6 2120.97    79.5 2119.53   139.1 2117.27
     169 2118.81   198.8 2117.96   238.5 2115.48   298.2 2109.34     328 2109.07
     338    2107   367.9  2097.6   377.9 2093.67   417.8  2073.8   427.8 2071.04
   437.8 2069.99   502.7 2068.01   507.7 2067.94   512.7 2068.92   517.7  2069.9
   547.6 2084.99   587.5 2102.56   646.7 2130.57   695.9 2152.64   715.6 2162.19
   735.3 2172.97   764.9 2191.46   794.4 2212.24     824 2235.07   883.1 2282.14
#Mann= 3 , 0 , 0
       0      .1       0   502.7    .045       0   512.7      .1       0
Bank Sta=502.7,512.7
XS Rating Curve= 0 ,0
Exp/Cntr=0.3,0.1

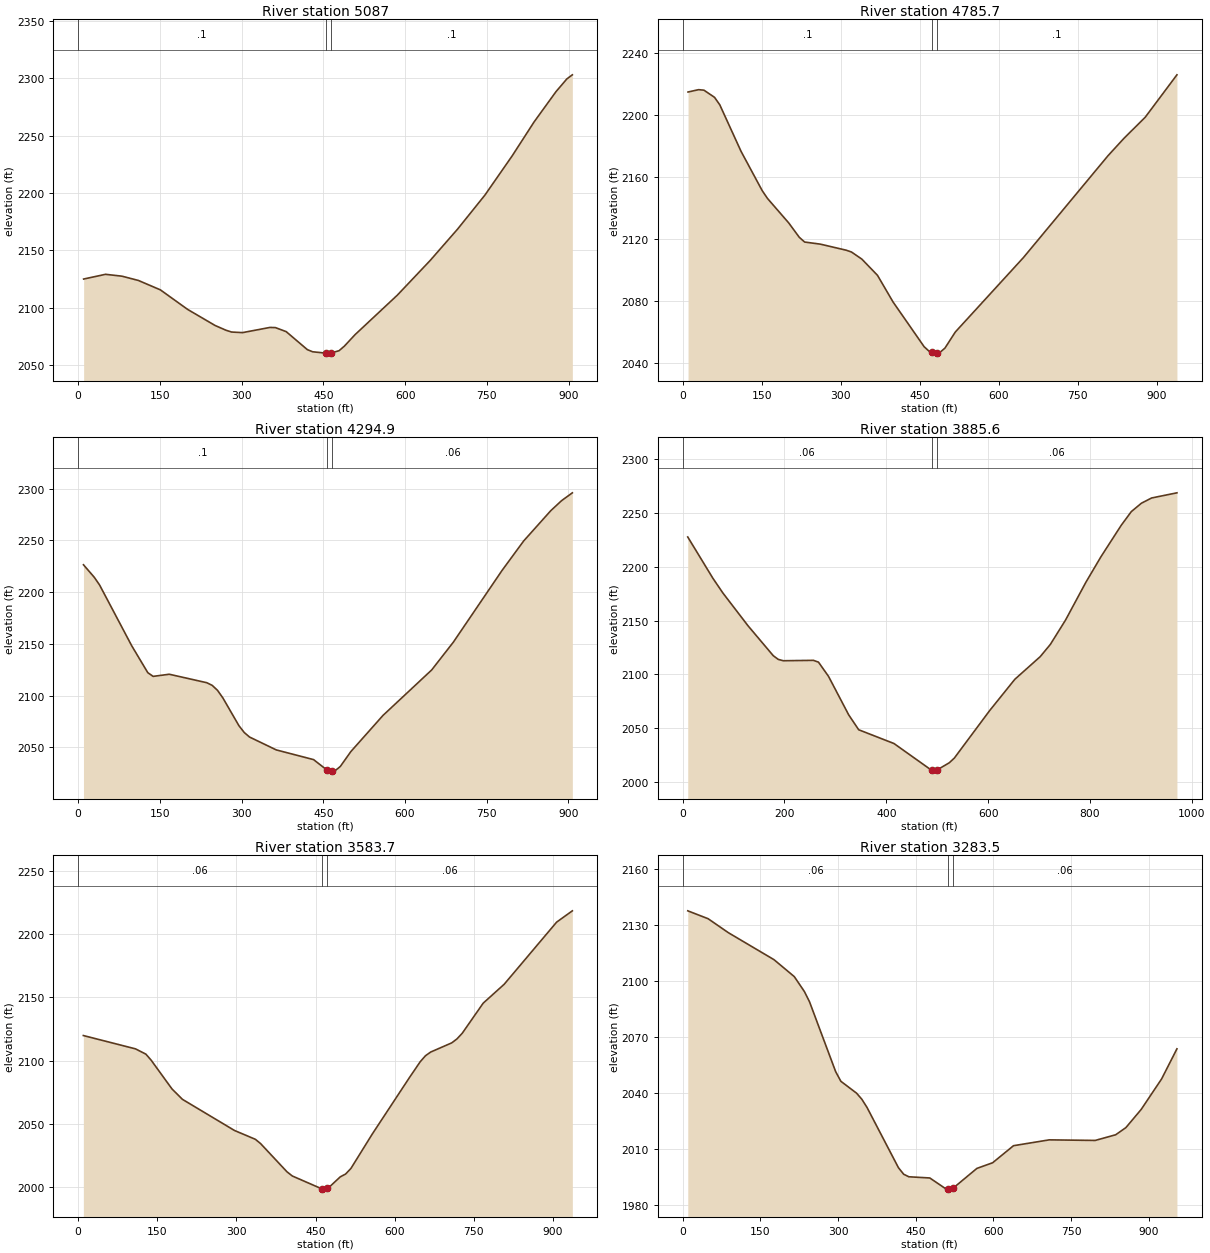
Type RM Length L Ch R = 1 ,5087    ,296.5,301.3,306.1
XS GIS Cut Line= 4
     1858699.834      154842.322     1858411.746       155077.84
     1858308.707      155264.992     1858077.395      155487.893
#Sta/Elev= 30
    10.1 2125.08    50.3 2129.21    80.5 2127.57   110.6 2123.85   150.9 2115.67
   201.1 2098.58   251.4  2084.6   271.5 2080.44   281.6 2078.91   301.7 2078.39
     352 2082.91     362 2082.77   381.8 2079.26   420.7 2063.55   430.4 2061.69
   454.5 2060.53   459.5 2060.52   464.5 2060.65   478.9 2062.64   488.6 2066.61
   508.1 2076.56   585.7 2110.99     646 2141.23   696.2 2168.49   746.4 2198.15
   796.6 2232.45   836.7 2261.95   876.9 2288.35   896.9 2299.48     907 2303.06
#Mann= 3 , 0 , 0
       0      .1       0   454.5    .045       0   464.5      .1       0
Bank Sta=454.5,464.5
XS Rating Curve= 0 ,0
Exp/Cntr=0.3,0.1

Type RM Length L Ch R = 1 ,4785.7  ,492.1,490.8,489.6
XS GIS Cut Line= 4
      1858533.71      154726.666     1858291.884      154796.059
     1858064.778      155042.091     1857917.579      155361.722
#Sta/Elev= 30
    10.1 2214.96    30.2 2216.47    40.3 2216.14    60.4 2211.53    70.4 2206.69
   110.7 2176.71     151 2151.26     161 2146.25   201.3 2130.45   221.4 2121.16
   231.5 2118.13   261.4 2116.76   310.7 2112.84   320.5 2111.67   340.2 2107.07
   369.8 2096.65   399.3 2079.47   458.4 2050.56   468.2 2047.53   473.1 2046.98
   478.1 2046.43   483.1 2046.61   487.9 2046.79   497.8 2049.63   517.5 2060.04
   646.7 2108.04   807.6  2173.9   837.8 2185.09     878 2198.64   938.3 2226.05
#Mann= 3 , 0 , 0
       0      .1       0   473.1    .045       0   483.1      .1       0
Bank Sta=473.1,483.1
XS Rating Curve= 0 ,0
Exp/Cntr=0.3,0.1

Type RM Length L Ch R = 1 ,4294.9  ,411.1,409.3,407.5
XS GIS Cut Line= 4
     1858141.268      154348.418     1857902.071      154485.103
      1857723.33        154705.9     1857429.477      154891.619
#Sta/Elev= 30
     9.8 2226.41    29.5 2214.42    39.4 2206.87    98.4 2148.13   127.9 2122.15
   137.7 2118.59   167.3 2120.64   236.1 2112.47     246 2109.94   255.8 2105.13
   265.7 2097.77   295.1 2070.99   304.9 2064.36   314.7 2059.97   363.7 2047.54
   432.2 2038.16   456.6 2028.17   461.6 2027.04   466.6 2027.19   471.4 2027.33
   481.2  2031.5   500.8 2046.05   559.6 2080.85     649 2124.79   688.7  2151.6
   778.1 2220.89   817.8 2249.38   867.5 2278.61   887.3  2288.3   907.2 2295.92
#Mann= 3 , 0 , 0
       0      .1       0   456.6    .045       0   466.6     .06       0
Bank Sta=456.6,466.6
XS Rating Curve= 0 ,0
Exp/Cntr=0.3,0.1

Type RM Length L Ch R = 1 ,3885.6  ,302.5,301.8,301.2
XS GIS Cut Line= 4
     1857852.128      154090.821     1857586.645      154198.591
     1857410.533      154461.446     1857347.448      154824.185
#Sta/Elev= 30
     9.9 2227.54    59.3 2189.22      79 2175.52   128.4 2145.07   177.8 2117.41
   187.7 2113.91   197.6 2112.66   256.9 2113.03   266.8 2111.34   286.5 2098.17
   326.1 2062.47   345.8 2048.59   415.1 2035.82   489.2 2010.93   494.2 2010.19
   499.2 2011.12   523.8 2017.95   533.7  2022.3   602.9 2066.25   652.7 2095.49
   702.4 2116.42   722.3 2127.77   752.2 2150.39     792 2185.33   821.8  2209.2
   861.6 2238.36   881.5 2251.13   901.4 2258.91   921.4 2263.75   971.1 2268.53
#Mann= 3 , 0 , 0
       0     .06       0   489.2    .045       0   499.2     .06       0
Bank Sta=489.2,499.2
XS Rating Curve= 0 ,0
Exp/Cntr=0.3,0.1

Type RM Length L Ch R = 1 ,3583.7  ,295.6,300.2,304.8
XS GIS Cut Line= 4
     1857534.074      153867.395     1857265.963      154130.249
     1857121.393      154361.561      1857071.45      154645.444
#Sta/Elev= 30
     9.9  2119.9   108.7 2109.37   128.4 2105.19   138.3 2100.46   177.9 2077.66
   197.6 2069.48   296.4 2044.82   335.9 2037.86   345.8 2034.46   395.7 2012.19
   405.8 2008.88   461.4 1998.77   466.4 1998.48   471.4 1999.39   476.5 2000.31
   496.7 2008.18   506.8  2010.4   516.9 2014.82   557.3 2041.97     628 2086.79
   648.2 2099.17   658.2 2103.93   668.1 2106.86   707.9 2114.09   717.8 2117.21
   727.8 2121.67   767.5 2145.47   807.3 2160.42   906.7 2209.55   936.5 2218.49
#Mann= 3 , 0 , 0
       0     .06       0   461.4    .045       0   471.4     .06       0
Bank Sta=461.4,471.4
XS Rating Curve= 0 ,0
Exp/Cntr=0.3,0.1

Type RM Length L Ch R = 1 ,3283.5  ,550.2,558.5,566.8
XS GIS Cut Line= 4
     1857400.019      153778.024     1857163.449      153841.109
     1856884.824      154119.735     1856813.853      154427.275
#Sta/Elev= 30
     9.8 2137.39      49 2133.17    88.1 2125.69   176.3 2111.22   215.5 2102.14
     235 2094.15   244.8 2088.73   295.4 2051.22   305.5 2046.04   335.8 2039.68
   345.9 2036.45     356 2032.02   416.6 1999.78   426.7 1996.26   436.8 1994.88
   477.2 1994.25   507.5 1988.55   512.6 1988.41   517.6 1988.27   522.6 1988.87
   568.1 1999.37   598.5 2002.39   638.9 2011.54   707.9 2014.67   796.7 2014.36
   836.1 2017.39   855.9 2021.22   885.5 2030.99   924.9 2047.32   954.5 2063.44
#Mann= 3 , 0 , 0
       0     .06       0   512.6    .045       0   522.6     .06       0
Bank Sta=512.6,522.6
XS Rating Curve= 0 ,0
Exp/Cntr=0.3,0.1

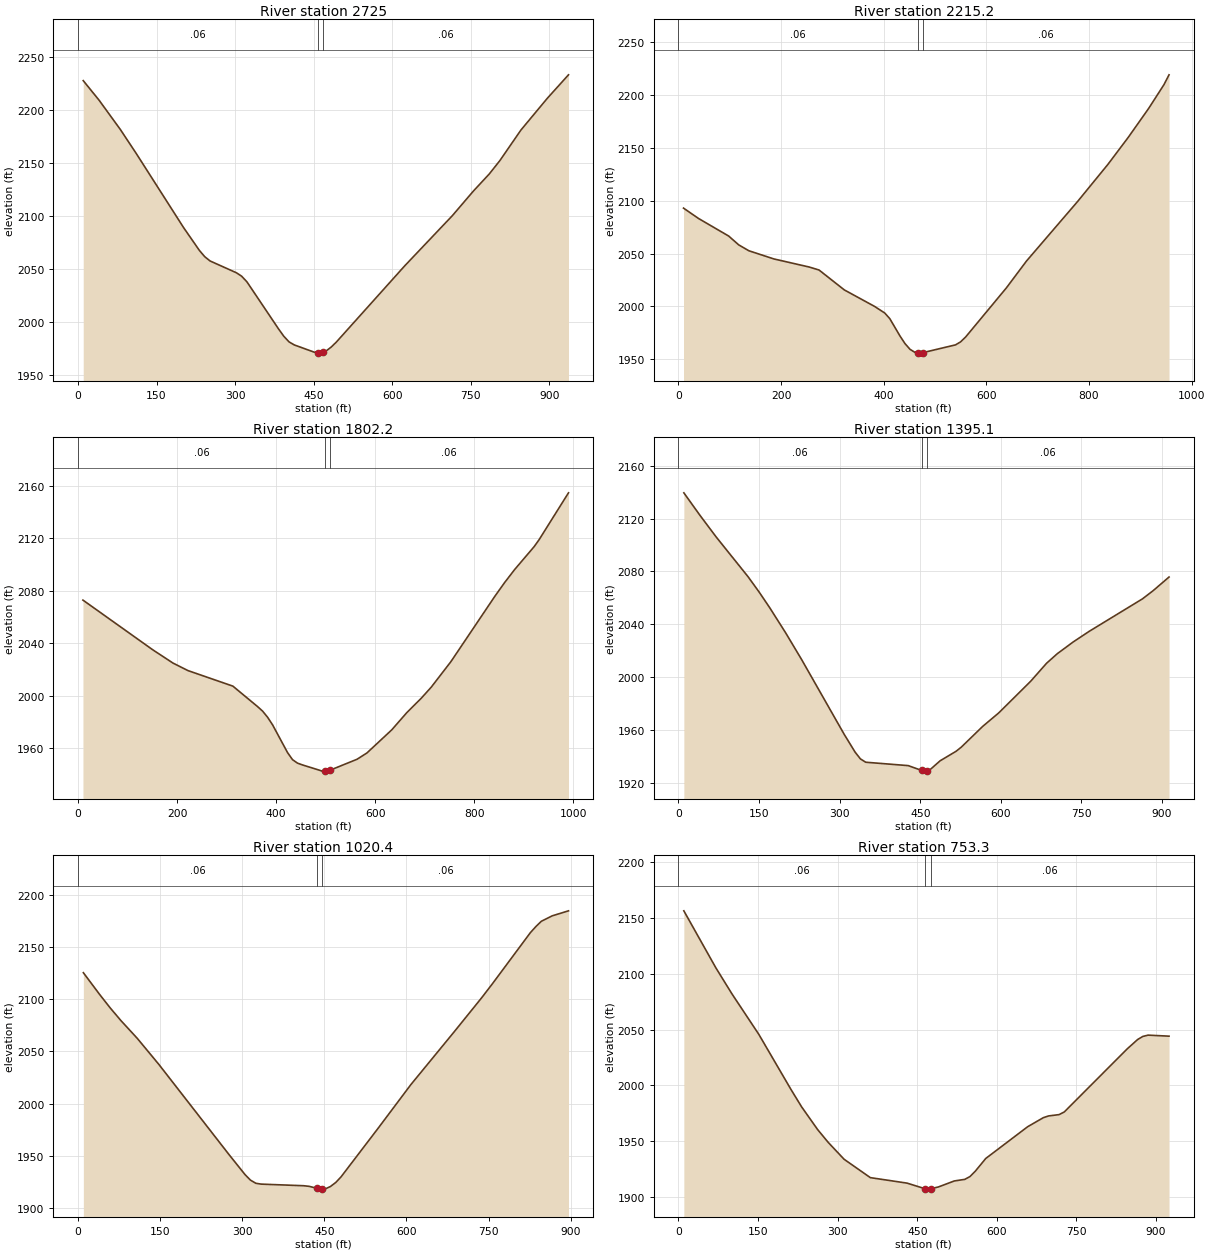
Type RM Length L Ch R = 1 ,2725    ,509.2,509.8,510.5
XS GIS Cut Line= 4
     1857194.992      153465.227     1856933.052      153452.348
     1856595.684      153583.512     1856374.886      153804.309
#Sta/Elev= 30
    10.1 2227.99    40.3 2209.54    80.7    2182     111 2159.38   201.7 2089.12
     232 2067.47   242.1 2061.62   252.2 2057.61   302.5 2046.46   312.5 2043.21
   322.6 2037.88   382.9 1993.45     393 1986.47     403 1981.14   413.1 1978.26
   453.3 1971.03   458.4 1970.77   463.4 1970.52   468.4 1971.47   473.4 1972.42
   483.5 1976.25   493.5 1981.08   624.2 2053.18   714.9 2100.46   755.2 2123.79
   785.4 2139.88   805.5 2152.43   845.8 2181.37   896.2 2211.37   936.5 2233.47
#Mann= 3 , 0 , 0
       0     .06       0   458.4    .045       0   468.4     .06       0
Bank Sta=458.4,468.4
XS Rating Curve= 0 ,0
Exp/Cntr=0.3,0.1

Type RM Length L Ch R = 1 ,2215.2  ,427.2,413,398.8
XS GIS Cut Line= 4
     1857063.565      153015.746     1856793.313      152971.035
     1856490.542      153089.345     1856232.945      153336.428
#Sta/Elev= 30
     9.8 2093.06    39.1 2083.24    97.8 2066.64   117.4 2058.29     137 2052.75
   185.9 2044.98   254.4 2037.37   273.9 2034.51   323.2 2015.67   382.3 2000.02
     402  1993.8   411.8 1988.48   431.5 1972.19   441.4  1964.9   451.2 1959.48
   461.1 1956.48   465.9 1956.19   470.9 1955.88   475.9  1956.3   539.9  1963.7
   549.7 1966.52   559.6 1971.16   638.7 2017.44   678.3 2043.09   777.5 2099.18
     837 2134.55   876.6 2160.09   916.3 2187.42     946 2209.83   955.9 2219.14
#Mann= 3 , 0 , 0
       0     .06       0   465.9    .045       0   475.9     .06       0
Bank Sta=465.9,475.9
XS Rating Curve= 0 ,0
Exp/Cntr=0.3,0.1

Type RM Length L Ch R = 1 ,1802.2  ,402,407.1,412.1
XS GIS Cut Line= 4
     1856750.768      152490.037     1856451.114      152579.407
      1856277.63      152884.319     1855984.928      153029.251
#Sta/Elev= 30
    10.1  2072.8   151.3 2034.83   191.7 2024.82   221.9 2019.08   312.7 2007.21
   362.8 1991.53   372.8 1988.11   382.9 1983.41   392.9 1977.66     423 1956.57
     433 1951.19     443 1948.52     453 1947.15   493.1 1942.43   498.1 1942.41
   503.1  1942.4   508.1 1942.99   563.3 1951.44   583.3 1956.26   633.4 1973.87
   663.5 1986.89   693.2 1998.09     713 2006.39   752.6 2025.79   841.7 2075.83
   861.5 2086.32   881.3 2096.05   920.8 2113.57   930.7 2118.81   990.1 2154.59
#Mann= 3 , 0 , 0
       0     .06       0   498.1    .045       0   508.1     .06       0
Bank Sta=498.1,508.1
XS Rating Curve= 0 ,0
Exp/Cntr=0.3,0.1

Type RM Length L Ch R = 1 ,1395.1  ,375.5,374.7,373.9
XS GIS Cut Line= 4
     1856352.012      152127.342     1856184.544      152338.264
     1855964.833      152566.265     1855786.555      152840.376
#Sta/Elev= 30
      10 2139.46    39.9 2122.47    69.8 2106.22   129.7 2075.82   149.6 2064.61
   169.6 2052.58   199.5  2033.4   229.4 2013.03   308.9 1956.22   328.7  1943.1
   338.6 1937.97   348.5 1935.45   427.6 1932.88   452.3 1929.27   457.3 1928.71
   462.3  1929.1   467.2 1929.47     487 1936.56   516.7 1943.76   526.6 1946.99
   566.2 1962.61   595.9 1972.77   655.3 1996.71     685  2010.4   704.9 2017.62
   734.6 2026.54   764.3 2034.56   863.4 2059.15   883.2 2065.32   912.9  2075.7
#Mann= 3 , 0 , 0
       0     .06       0   452.3    .045       0   462.3     .06       0
Bank Sta=452.3,462.3
XS Rating Curve= 0 ,0
Exp/Cntr=0.3,0.1

Type RM Length L Ch R = 1 ,1020.4  ,267.7,267,266.4
XS GIS Cut Line= 4
     1856106.774        151906.5     1855878.091      152108.898
     1855709.864      152298.153     1855523.237      152579.407
#Sta/Elev= 30
     9.9 2125.29    39.4 2104.62    59.1 2091.46    78.8 2079.27   108.4 2062.42
   147.8 2037.49   275.8 1951.25   305.4 1931.87   315.1 1926.69   324.9 1923.67
   334.6 1922.85   412.5 1921.29   422.3 1920.73   436.7 1918.84   441.7 1918.05
   446.7 1918.13   451.5 1918.21   461.2 1920.55     471 1924.45   480.7 1929.85
   548.9 1976.72   608.2 2018.16   687.7 2068.96   737.3 2101.16   757.2 2114.76
   826.6 2163.73   836.6 2169.51   846.5 2174.53   866.4 2179.75   896.1 2184.54
#Mann= 3 , 0 , 0
       0     .06       0   436.7    .045       0   446.7     .06       0
Bank Sta=436.7,446.7
XS Rating Curve= 0 ,0
Exp/Cntr=0.3,0.1

Type RM Length L Ch R = 1 ,753.3   ,209.9,208.8,207.7
XS GIS Cut Line= 4
     1855924.046      151721.318     1855702.657      151896.841
     1855512.723      152124.669     1855202.044      152275.412
#Sta/Elev= 30
    10.1 2156.37    70.6 2105.21   100.9 2081.94   151.4 2045.79   211.9 1996.54
   232.1 1980.85   262.3 1960.51   282.5  1948.9   312.2 1933.93   361.6 1917.51
   430.8 1912.59   465.4 1907.47   470.4 1907.22   475.4 1907.55   490.2 1909.22
   519.8 1914.53   539.6 1915.95   549.5 1918.52   559.4 1923.29   579.1 1934.66
   658.1  1963.1   687.7  1971.2   697.5 1972.75   717.3 1973.93   727.1 1976.32
   845.5  2032.7   865.3 2041.14   875.1 2043.91     885 2045.08   924.5 2044.16
#Mann= 3 , 0 , 0
       0     .06       0   465.4    .045       0   475.4     .06       0
Bank Sta=465.4,475.4
XS Rating Curve= 0 ,0
Exp/Cntr=0.3,0.1

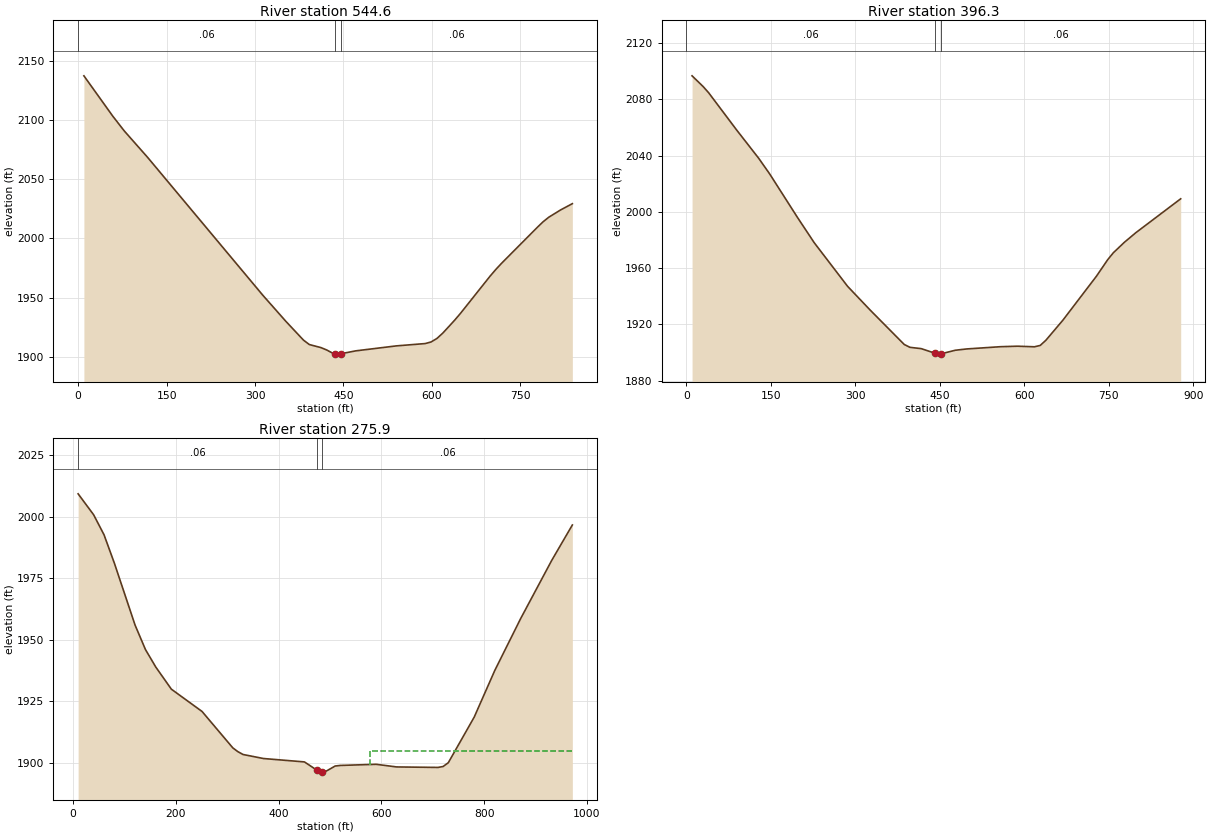
Type RM Length L Ch R = 1 ,544.6   ,149.5,148.3,147
XS GIS Cut Line= 4
     1855746.664      151564.789     1855533.752      151767.187
     1855357.639      152003.756     1855236.726      152221.925
#Sta/Elev= 30
     9.8 2137.08    58.8 2103.05    78.3 2090.58   117.5 2068.51   313.4 1951.93
   352.7 1929.82   382.2 1914.17   392.1 1910.46   411.7 1907.89   421.6 1905.86
   431.4 1903.26   436.2 1902.83   441.2 1902.38   446.2 1902.76   470.7 1905.13
   539.5 1909.32   588.7 1911.29   598.7 1912.67   608.6 1915.63   618.6  1920.2
   638.6 1931.03   648.6 1936.88   698.4 1968.01   708.4 1973.83   718.4 1979.14
   778.3  2009.1   788.2 2013.86   798.2 2017.85   818.2 2023.98   838.1 2029.26
#Mann= 3 , 0 , 0
       0     .06       0   436.2    .045       0   446.2     .06       0
Bank Sta=436.2,446.2
XS Rating Curve= 0 ,0
Exp/Cntr=0.3,0.1

Type RM Length L Ch R = 1 ,396.3   ,120.7,120.4,120.1
XS GIS Cut Line= 4
     1855638.893      151483.304     1855415.467      151662.045
      1855228.84      151948.557     1855194.669       152195.64
#Sta/Elev= 30
     9.9 2096.63    29.6    2089    39.5 2084.53    88.8 2058.28   128.3    2038
     148 2026.76   197.3 1995.88   226.9 1978.02   286.1 1947.06   326.4  1930.1
   386.7 1905.73   396.8 1903.74   416.9  1902.8     442 1899.45     447 1898.91
     452 1899.13   477.2 1901.66   497.3 1902.58   557.7 1904.19   587.8 1904.54
     618 1904.12   628.1  1905.1     638 1908.71     668 1922.86   727.8 1954.22
   747.8 1965.95   757.8 1970.89   777.7 1978.43   797.7 1985.14   877.5 2009.27
#Mann= 3 , 0 , 0
       0     .06       0     442    .045       0     452     .06       0
Bank Sta=442,452
XS Rating Curve= 0 ,0
Exp/Cntr=0.3,0.1

Type RM Length L Ch R = 1 ,275.9   ,273,275.9,278.8
XS GIS Cut Line= 4
     1855520.609      151349.248     1855383.924      151483.304
     1855149.984      151853.929      1855139.47       152195.64
#Sta/Elev= 30
    10.1 2009.38    40.3 2000.86    60.5 1992.73    80.6  1981.2   120.9 1956.02
   141.1 1946.08   161.2 1938.96   191.5 1929.97   251.2 1920.91     311 1906.12
   320.9 1904.57   330.9 1903.42   370.7 1901.78   450.4  1900.4   475.3 1896.96
   480.3 1896.25   485.3 1896.31   490.3 1896.36   510.2 1898.73   520.2 1898.97
   589.9 1899.43   629.7 1898.36   710.2 1898.16   720.2 1898.54   730.3 1900.08
   780.6 1918.58   820.8 1937.61   871.1 1958.69   931.4 1982.29   971.6 1996.71
#Mann= 3 , 0 , 0
    10.1     .06       0   475.3    .045       0   485.3     .06       0
#XS Ineff= 2 , 0
                          577.77         1904.96
Permanent Ineff=
       F       F
Bank Sta=475.3,485.3
XS Rating Curve= 0 ,0
Exp/Cntr=0.3,0.1

Chan Stop Cuts=-1
Use User Specified Reach Order=0